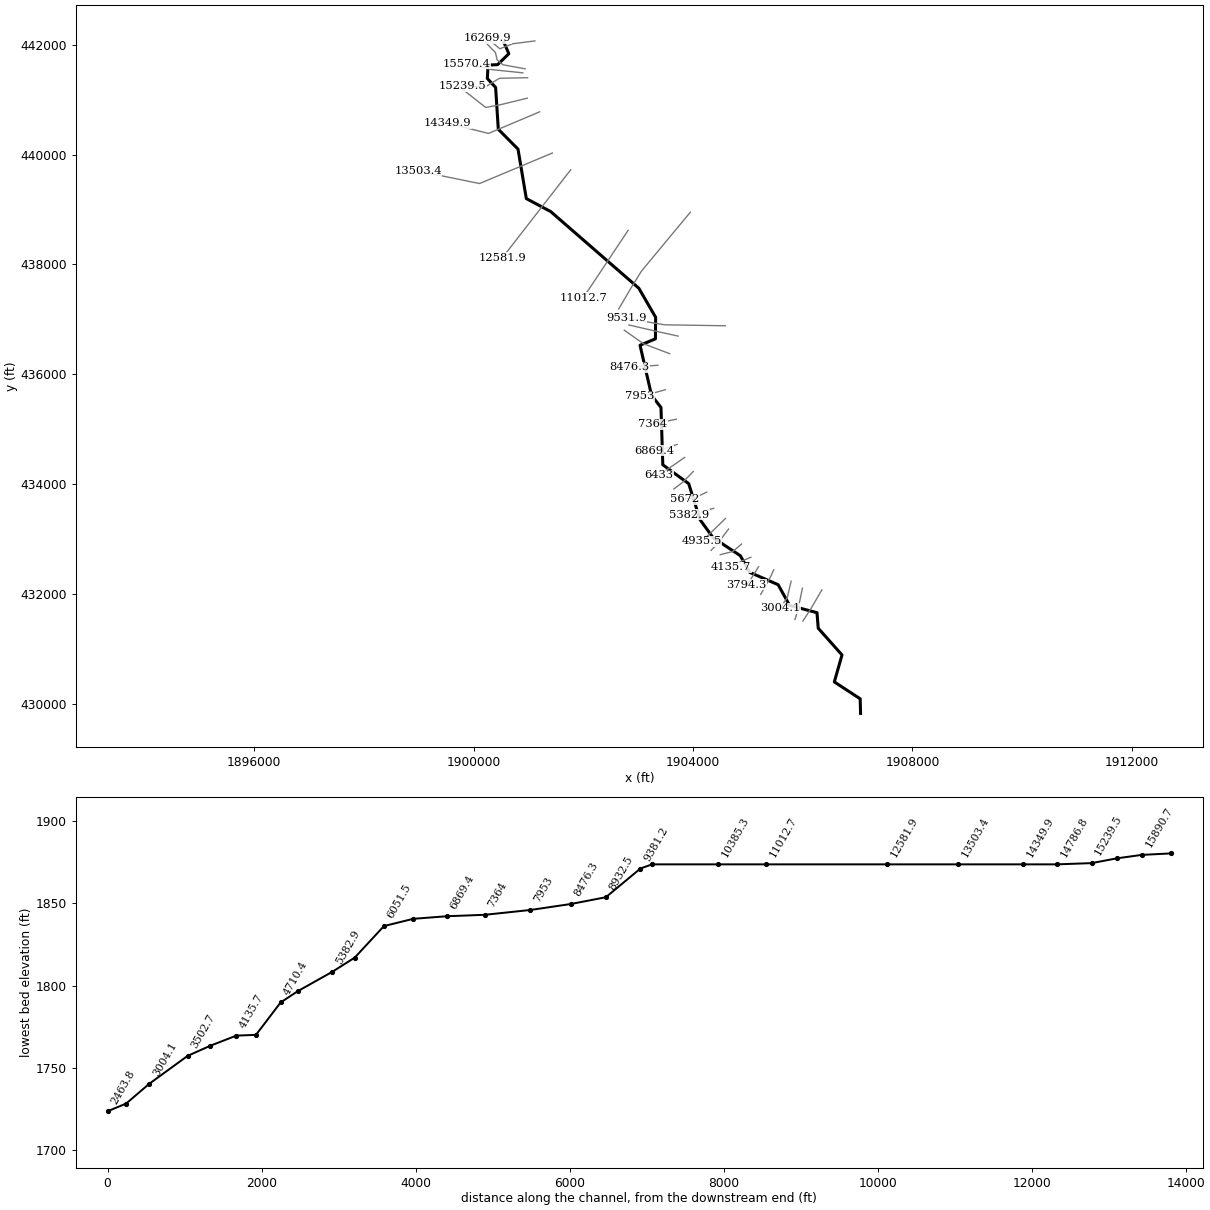
--- PATTERSNRN.prj (project) ---

Proj Title=PATTERSNRN
Current Plan=p01
Default Exp/Contr=0,0
English Units
Geom File=g01
Flow File=f01
Plan File=p01
BEGIN DESCRIPTION:
END DESCRIPTION:
DSS Export Rating Curves= 0
DSS Export Rating Curve Sorted= 0
DSS Export Volume Flow Curves= 0
DXF OffsetX= 0
DXF OffsetY= 0
DXF ScaleX= 0
DXF ScaleY= 0

--- PATTERSNRN.p01 (plan) ---

Plan Title=Floodplain
Program Version=4.00
Geom File=g01
Flow File=f01
K Sum by GR=0
Std Step Tol=0.01
Critical Tol=0.01
Num of Std Step Trials=20
Max Error Tol=0.3
Flow Tol Ratio=0.001
Split Flow NTrial=30
Split Flow Tol=0.02
Split Flow Ratio=0.02
Log Output Level=0
Friction Slope Method=1
Unsteady Friction Slope Method=2
Unsteady Bridges Friction Slope Method=1
Global Log Level=0
CheckData=False
Run HTab=0
Run UNet=0
Run PostProcess=0
UNET Theta=0
UNET Theta Warmup=0
UNET ZTol=0
UNET ZSATol=0
UNET MxIter=0
UNET MaxInSteps=0
UNET DtIC=0
UNET DtMin=0
UNET MaxCRTS=0
UNET WFStab=0
UNET SFStab=0
UNET WFX=0
UNET SFX=0
UNET DSS MLevel=0
UNET DZMax Abort=0
UNET Convert EG Bridges=0
UNET Use Existing IB Tables=0
UNET Froude Limit=0
UNET Froude Power=0
Write IC File=0
Echo Input=False
Echo Output=False
Write Detailed=0

--- PATTERSNRN.f01 (steady flow) ---

Flow Title=NFF Regression Equation
Program Version=4.00
Number of Profiles=1
Profile Names=P100yr
River Rch & RM=PATTERSNRN,Main      ,16269.9
654.6079
River Rch & RM=PATTERSNRN,Main      ,13503.4
728.8867
River Rch & RM=PATTERSNRN,Main      ,12581.9
895.0631
River Rch & RM=PATTERSNRN,Main      ,11012.7
923.4847
River Rch & RM=PATTERSNRN,Main      ,9531.9
1025.524
River Rch & RM=PATTERSNRN,Main      ,77.6
1132.268
Boundary for River Rch & Prof#=PATTERSNRN,Main      ,1
Up Type=0
Dn Type=3
Dn Slope=0.037503

--- PATTERSNRN.g01 (geometry) ---

Geom Title=USGS 10m DEM
Program Version=4.10

River Reach=PATTERSNRN      ,Main
Reach XY= 30
     1900555.147      442040.733     1900643.688      441834.135
     1900439.576       441635.03     1900265.217      441627.913
     1900252.195      441382.747      1900403.02      441221.071
     1900452.022      440460.293     1900811.397      440098.314
     1900962.699      439198.791     1901407.143       438962.68
     1903013.046      437568.583     1903320.338      437039.069
     1903315.761      436647.182     1903035.615      436530.388
     1903245.685       435618.93      1903417.56      435398.444
     1903450.546      434355.909     1903922.768      434013.027
     1904129.365      433357.645     1904366.293      433030.634
      1904863.74      432702.263     1905033.879       432400.18
     1905552.976      432174.486     1905762.688      431797.866
     1906261.371      431665.586     1906283.879      431382.819
     1906717.476      430896.364     1906577.282      430406.256
     1907048.495      430098.866     1907055.776      429833.764

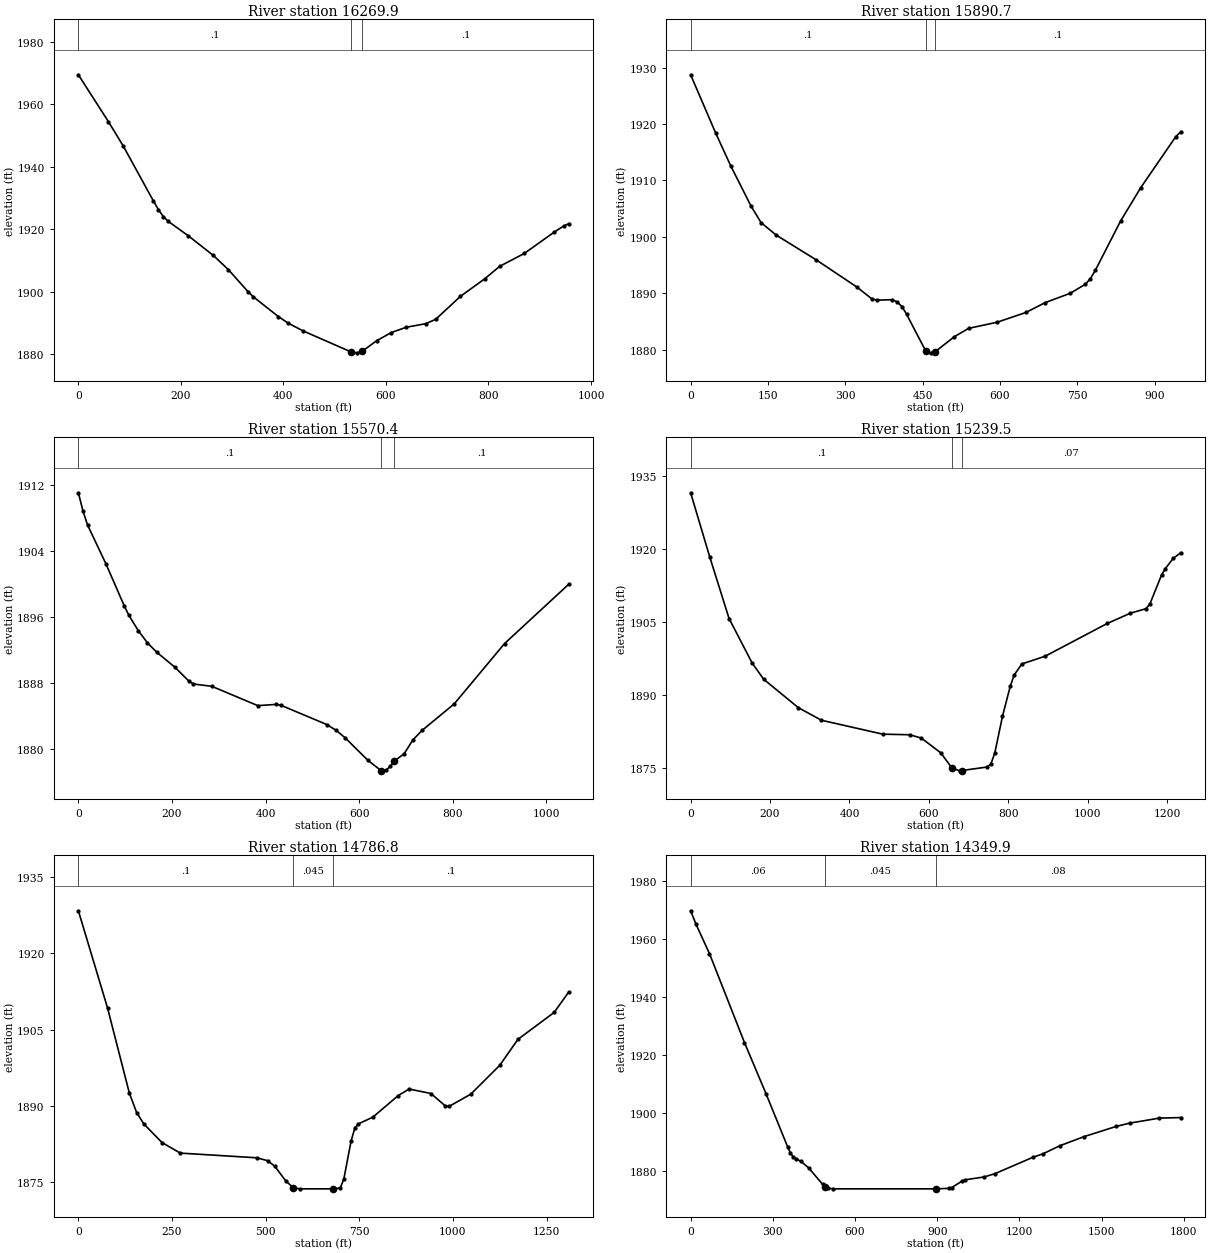
Type RM Length L Ch R = 1 ,16269.9 ,403.7,379.3,354.8
XS GIS Cut Line= 4
     1901118.688      442067.064     1900712.438       442014.98
     1900480.667      441923.835     1900251.501      442113.939
#Sta/Elev= 30
       0 1969.41    58.5 1954.43    87.8 1946.53   146.3 1929.03     156 1926.26
   165.8 1923.98   175.5 1922.44   214.5 1917.84   263.3 1911.55   292.6 1907.01
   331.6 1899.83   341.3  1898.3   390.1 1891.98   409.6 1889.84   438.3 1887.39
  531.191880.707   543.7 1880.36   553.3  1880.8     582 1884.26   610.7 1886.87
   639.5 1888.55   677.8  1889.7     697 1891.09   745.1 1898.42   793.1 1904.12
   821.9 1908.07   869.9 1912.19   927.6 1918.95   946.8    1921   956.4 1921.69
#Mann= 3 , 0 , 0
       0      .1       0  531.19    .045       0   553.3      .1       0
Bank Sta=531.19,553.3
XS Rating Curve= 0 ,0
Exp/Cntr=0.3,0.1

Type RM Length L Ch R = 1 ,15890.7 ,309.9,320.2,330.5
XS GIS Cut Line= 5
     1900941.605      441559.251      1900538.52      441632.854
     1900431.188       441720.71     1900399.938      441856.126
     1900215.042      442043.626
#Sta/Elev= 30
       0 1928.72    48.8 1918.35      78 1912.54   117.1 1905.47   136.6 1902.53
   165.8 1900.33   243.9 1895.91     322 1891.14   351.2 1889.04     361  1888.8
   390.2 1888.87     400 1888.51   409.8 1887.66     419 1886.26   455.8 1879.81
   465.2 1879.46   474.5 1879.68   511.5 1882.32   539.2  1883.8   594.8 1884.89
   650.4 1886.62   687.4 1888.35   736.2 1890.01   765.4 1891.61   775.2 1892.59
     785  1894.1   833.7 1902.79   872.7 1908.69     941 1917.78   950.8 1918.63
#Mann= 3 , 0 , 0
       0      .1       0   455.8    .045       0   474.5      .1       0
Bank Sta=455.8,474.5
XS Rating Curve= 0 ,0
Exp/Cntr=0.3,0.1

Type RM Length L Ch R = 1 ,15570.4 ,308.8,330.9,348.9
XS GIS Cut Line= 4
     1900899.938      441486.335     1900342.647      441543.626
     1900191.605       441577.48     1899867.137      441649.325
#Sta/Elev= 30
       0 1911.05     9.8 1908.85    19.7 1907.14      59 1902.44    98.3 1897.32
   108.1  1896.2   127.8 1894.38   147.4  1892.9   167.1 1891.77   206.4 1889.93
   235.9 1888.27   245.7 1887.91     285 1887.63   383.3 1885.29   422.6 1885.44
   432.5 1885.34   530.7    1883   550.4 1882.31   569.9  1881.4   618.3 1878.68
   647.3  1877.4     657 1877.46   666.6 1877.95   674.5 1878.56   695.7 1879.46
     715 1881.17   734.6 1882.31     803 1885.51   910.5 1892.81  1047.3 1899.97
#Mann= 3 , 0 , 0
       0      .1       0   647.3    .045       0   674.5      .1       0
Bank Sta=647.3,674.5
XS Rating Curve= 0 ,0
Exp/Cntr=0.3,0.1

Type RM Length L Ch R = 1 ,15239.5 ,460.7,452.7,444.3
XS GIS Cut Line= 4
     1900985.876      441397.793     1900472.855      441387.376
     1900215.568      441230.266     1899795.772      441246.751
#Sta/Elev= 30
       0 1931.49    48.4 1918.26    96.8  1905.7   154.9 1896.58     184 1893.24
   271.1 1887.43   329.2 1884.84   484.1 1881.98     552 1881.86   581.2 1881.17
   629.8 1878.16     659 1874.95   678.4 1874.46  682.181874.514   746.5 1875.24
   756.2 1875.86     766 1878.12   785.4 1885.66   804.9  1891.8   814.6 1894.09
   834.1 1896.38   892.8 1897.97  1049.1 1904.68  1107.7  1906.8  1146.8 1907.72
  1156.6 1908.69  1185.9 1914.61  1195.6 1915.95  1215.2 1918.02  1234.7 1919.22
#Mann= 3 , 0 , 0
       0      .1       0     659    .045       0  682.18     .07       0
Bank Sta=659,682.18
XS Rating Curve= 0 ,0
Exp/Cntr=0.3,0.1

Type RM Length L Ch R = 1 ,14786.8 ,432.2,436.9,441.7
XS GIS Cut Line= 4
     1900980.667      441025.397     1900498.897       440908.21
     1900222.855      440856.126     1899803.584      441184.251
#Sta/Elev= 30
       0 1928.33    77.8 1909.26   136.1 1892.52   155.6 1888.69     175 1886.43
   223.6 1882.78   272.2 1880.72   476.4  1879.8   505.5 1879.23   524.9  1878.1
   553.9 1875.24   573.3 1873.96   590.8  1873.7   679.9  1873.7   699.2 1873.85
   708.9 1875.65   728.3 1883.14     738  1885.6   747.7 1886.46   786.4 1887.79
   854.2 1892.03   883.2 1893.31   941.3 1892.43     980 1889.98   989.7 1889.89
  1047.8  1892.3  1125.2 1897.97  1173.6 1903.06  1270.4 1908.36  1309.1 1912.34
#Mann= 3 , 0 , 0
       0      .1       0   573.3    .045       0   679.9      .1       0
Bank Sta=573.3,679.9
XS Rating Curve= 0 ,0
Exp/Cntr=0.3,0.1

Type RM Length L Ch R = 1 ,14349.9 ,846.2,846.5,846.8
XS GIS Cut Line= 3
     1901206.362      440777.133      1900274.07      440383.904
      1899519.73      440572.272
#Sta/Elev= 30
       0 1969.83    19.6 1965.19    68.8 1955.02   196.5 1924.27   275.1  1906.6
   353.6 1888.33   363.5 1886.23   373.3 1884.84   383.1 1884.13   402.8 1883.22
   432.2 1880.81   481.4 1875.27   491.2 1874.38     501 1873.91   520.6  1873.7
     894  1873.7   943.1 1873.86   952.9 1874.15   992.2 1876.46    1002 1876.82
  1070.9 1877.81  1110.2 1878.93    1248 1884.56  1287.4 1885.87  1346.4 1888.56
    1435 1891.72  1553.1 1895.28  1602.3 1896.41  1710.6 1898.15  1789.3 1898.34
#Mann= 3 , 0 , 0
       0     .06       0   491.2    .045       0     894     .08       0
Bank Sta=491.2,894
XS Rating Curve= 0 ,0
Exp/Cntr=0.3,0.1

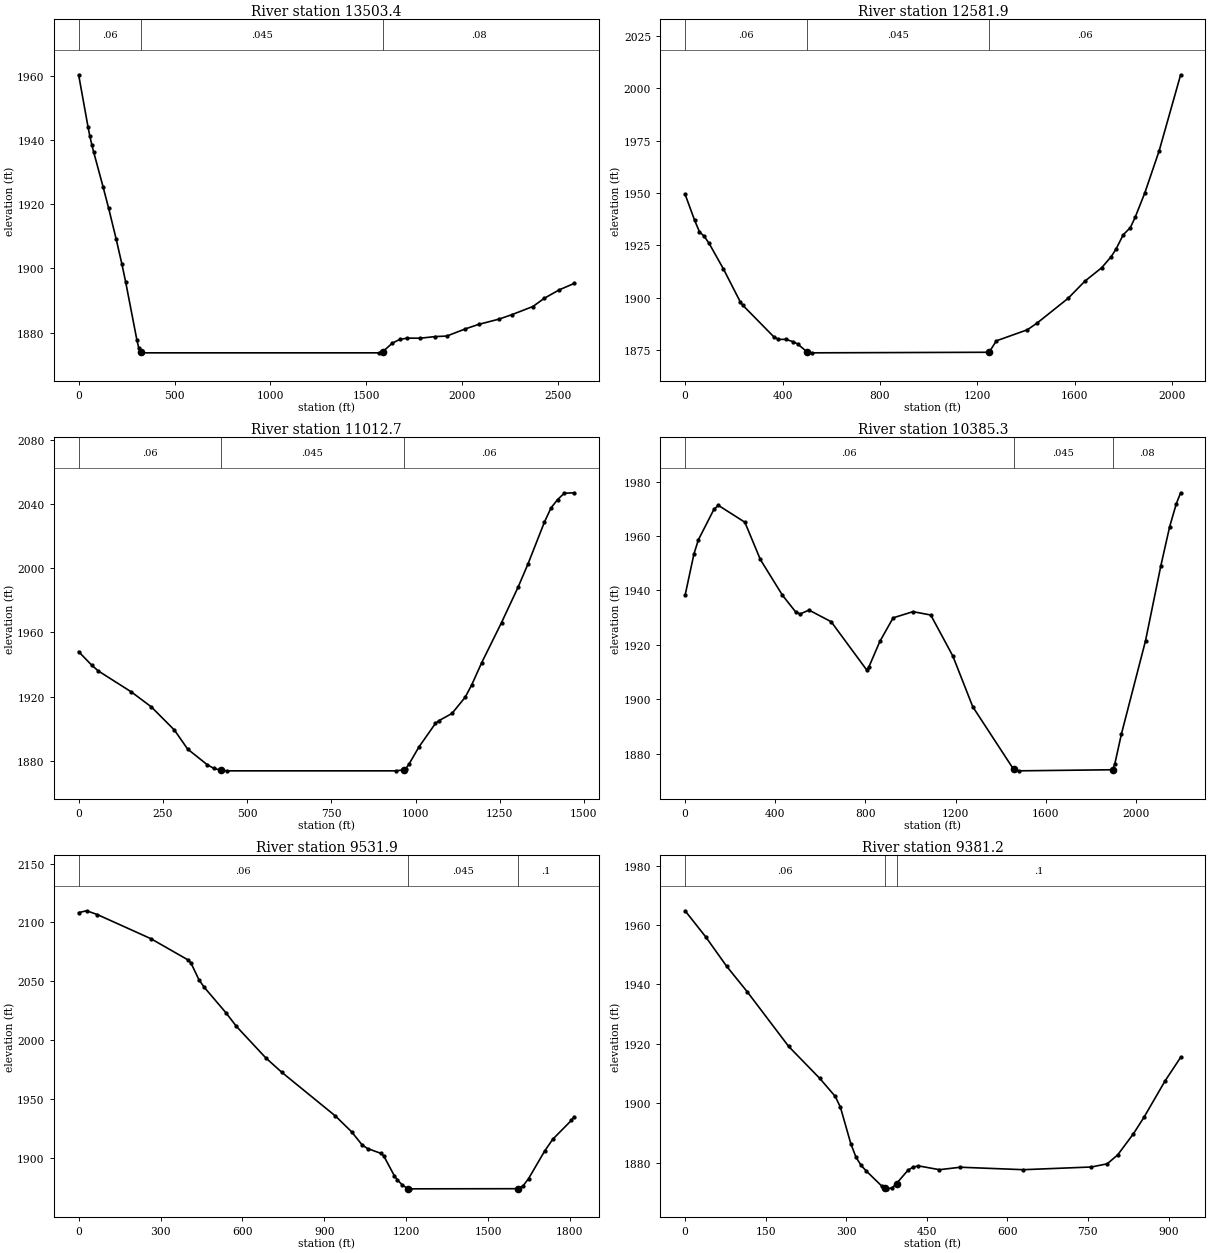
Type RM Length L Ch R = 1 ,13503.4 ,910.3,921.5,932.6
XS GIS Cut Line= 3
     1901438.567      440028.001     1900110.442      439472.446
     1898989.348      439700.657
#Sta/Elev= 30
       0 1960.25      49 1944.01    58.8 1941.04    68.6  1938.5    78.4 1936.21
   127.3 1925.39   156.7 1918.65   195.9 1909.06   225.2 1901.42   244.8 1895.89
   303.6 1877.74   313.4 1875.25   323.2 1873.98     333  1873.7  1566.8  1873.7
  1586.3 1874.08  1635.2  1876.7  1674.3 1877.88  1713.4 1878.27  1781.9 1878.26
  1860.1 1878.77  1918.8 1878.91  2016.6 1881.16    2085 1882.54  2192.6 1884.21
    2261 1885.63  2368.6 1888.12  2427.3 1890.66  2505.5  1893.3  2583.7  1895.3
#Mann= 3 , 0 , 0
       0     .06       0   323.2    .045       0  1586.3     .08       0
Bank Sta=323.2,1586.3
XS Rating Curve= 0 ,0
Exp/Cntr=0.3,0.1

Type RM Length L Ch R = 1 ,12581.9 ,1567.4,1569.1,1571
XS GIS Cut Line= 2
       1901771.9      439722.446       1900521.9      438116.543
#Sta/Elev= 30
       0 1949.37    39.3  1936.9      59 1931.46    78.6 1929.31    98.3 1925.99
   157.3 1913.76   226.1 1898.14     236 1896.52   363.8 1881.41   383.4 1880.11
   412.9 1880.14   442.4 1879.08   462.1 1877.94   501.4  1874.1     521  1873.7
  1248.6 1873.97    1278 1879.42  1405.8 1884.72  1445.2 1887.88    1573 1899.73
  1641.8 1907.91  1710.6  1914.3    1750 1919.64  1769.6  1923.2  1799.1 1930.02
  1828.6 1933.49  1848.3 1938.41  1887.6 1949.95  1946.6 1970.05    2035 2006.41
#Mann= 3 , 0 , 0
       0     .06       0   501.4    .045       0  1248.6     .06       0
Bank Sta=501.4,1248.6
XS Rating Curve= 0 ,0
Exp/Cntr=0.3,0.1

Type RM Length L Ch R = 1 ,11012.7 ,626.7,627.4,628
XS GIS Cut Line= 2
     1902818.775      438621.751     1902002.803      437397.793
#Sta/Elev= 30
       0 1947.95    39.2 1939.46    58.8 1935.88   156.9 1922.81   215.8 1913.54
   284.4 1899.08   323.6 1887.26   382.5 1877.39   402.1 1875.18   421.7  1874.1
   441.3  1873.7   941.4  1873.7  964.751874.279   970.9 1875.02   980.7 1877.89
  1010.1 1888.55  1059.1 1903.21  1068.9 1904.89  1108.2 1909.44  1147.4 1919.53
    1167 1927.31  1196.4 1941.04  1255.3 1966.05  1304.3 1988.03  1333.7 2002.48
  1382.8 2028.71  1402.4 2037.57    1422 2042.73  1441.6 2046.66    1471 2046.93
#Mann= 3 , 0 , 0
       0     .06       0   421.7    .045       0  964.75     .06       0
Bank Sta=421.7,964.75
XS Rating Curve= 0 ,0
Exp/Cntr=0.3,0.1

Type RM Length L Ch R = 1 ,10385.3 ,880.4,853.5,826.7
XS GIS Cut Line= 4
     1903952.456      438950.961     1903061.735      437879.186
     1902888.709      437601.639       1902646.9      437190.545
#Sta/Elev= 30
       0 1938.23    39.3 1953.45    58.9 1958.63   127.6 1969.77   147.2  1971.3
     265 1965.09   333.7 1951.39   431.8 1938.24   490.7 1932.07   510.3 1931.37
   549.6 1932.78   647.7 1928.52   804.8 1910.84   814.6  1911.8   863.6 1921.25
   922.5 1929.94  1010.8 1932.21  1089.4 1930.98  1187.5 1915.88  1275.8 1897.24
 1456.781874.263  1480.2  1873.7  1895.8  1874.1  1905.6  1876.2  1934.8 1887.18
  2041.8 1921.49    2110 1949.15  2148.9 1963.45  2178.1 1971.81  2197.6 1975.91
#Mann= 3 , 0 , 0
       0     .06       0 1456.78    .045       0  1895.8     .08       0
Bank Sta=1456.78,1895.8
XS Rating Curve= 0 ,0
Exp/Cntr=0.3,0.1

Type RM Length L Ch R = 1 ,9531.9  ,151.5,150.7,149.5
XS GIS Cut Line= 3
     1904591.344      436884.989     1903483.706       436902.35
     1902785.789      437020.406
#Sta/Elev= 30
       0 2108.35    29.4  2109.9    68.6 2106.68   264.7  2086.2   401.9 2068.01
   411.7 2065.45   441.2 2051.13   460.8 2044.74   539.2 2023.42   578.4 2011.63
   686.2 1984.82     745 1972.57   941.1 1935.53   999.9 1922.21  1039.2 1910.86
  1058.8 1907.91  1107.8 1903.82  1117.6  1901.8  1156.9 1884.74  1166.8 1881.57
  1186.4 1876.85  1206.1 1873.94  1215.9  1873.7  1609.2 1873.82  1628.8 1876.36
  1648.5 1882.38  1707.5 1905.82    1737  1915.8  1805.8 1931.94  1815.6 1934.99
#Mann= 3 , 0 , 0
       0     .06       0  1206.1    .045       0  1609.2      .1       0
Bank Sta=1206.1,1609.2
XS Rating Curve= 0 ,0
Exp/Cntr=0.3,0.1

Type RM Length L Ch R = 1 ,9381.2  ,456.4,448.7,440.2
XS GIS Cut Line= 3
     1903731.927      436696.929     1903355.233       436779.52
     1902831.796      436899.312
#Sta/Elev= 30
       0 1964.83    38.6 1955.99    77.1  1946.2   115.7 1937.55   192.8 1919.14
   250.7 1908.38   279.6 1902.29   289.2 1898.65   308.5 1886.39   318.2 1881.81
   327.8 1879.04   337.4 1877.17   366.4 1872.06  372.721871.474     376 1871.17
   385.6 1871.55   393.6 1872.96   414.9 1877.43   424.7 1878.52   434.5  1878.9
   473.5 1877.62   512.6 1878.45   629.7 1877.62   756.6 1878.53   785.9  1879.6
   805.4  1882.6   834.7 1889.72   854.3 1895.26   893.3 1907.43   922.6 1915.46
#Mann= 3 , 0 , 0
       0     .06       0  372.72    .045       0   393.6      .1       0
Bank Sta=372.72,393.6
XS Rating Curve= 0 ,0
Exp/Cntr=0.3,0.1

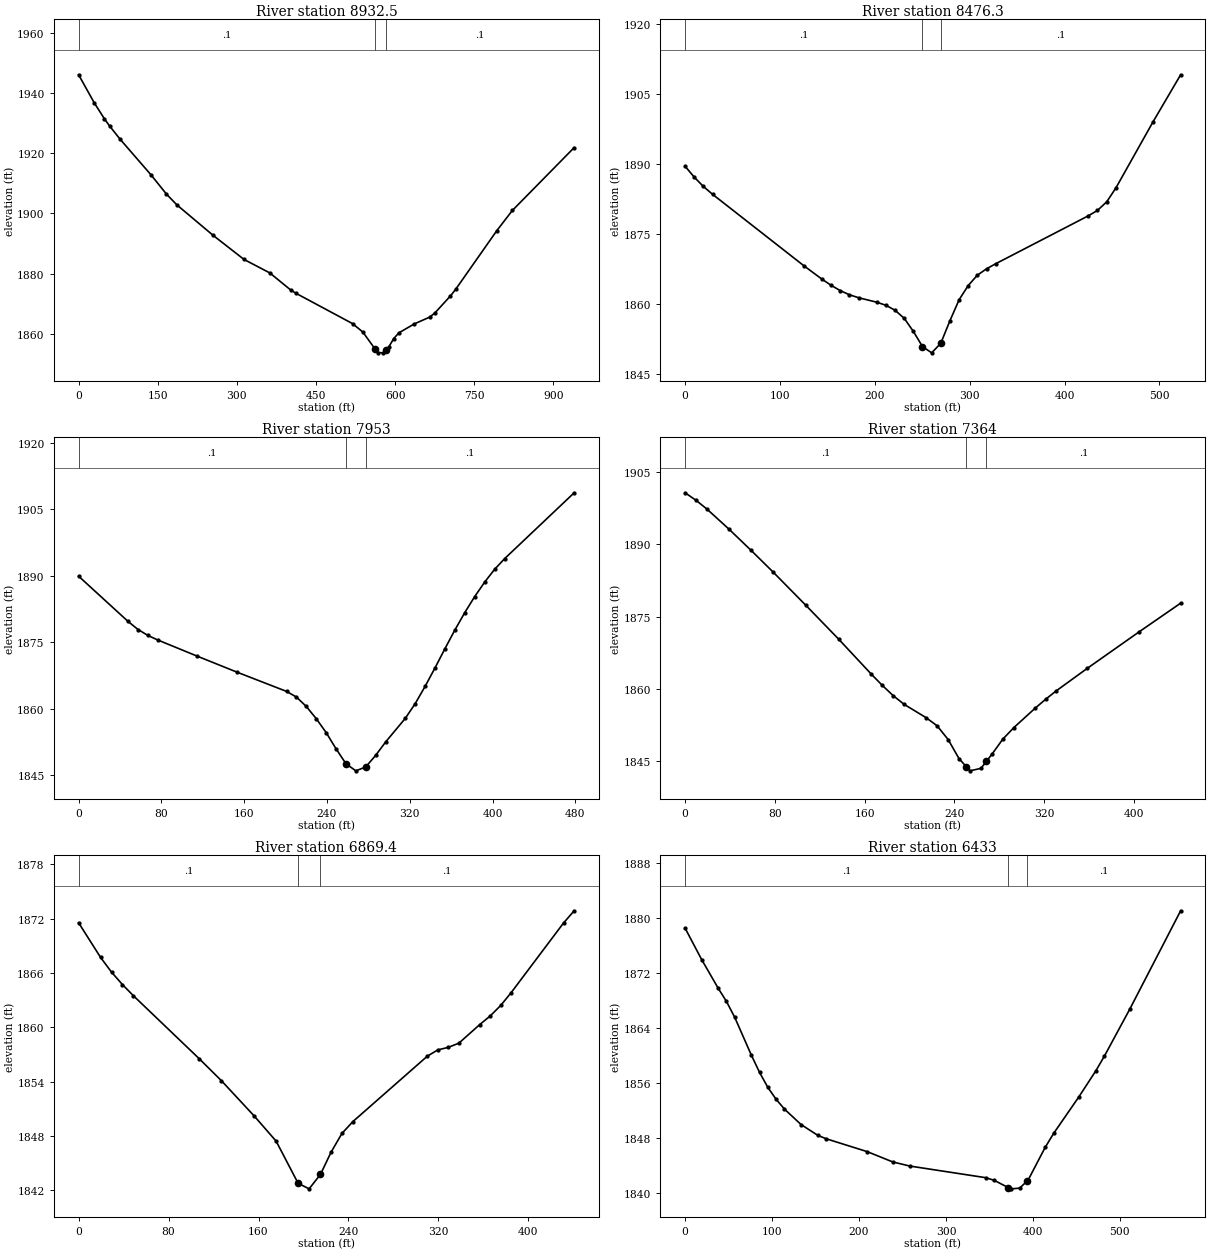
Type RM Length L Ch R = 1 ,8932.5  ,441.4,456.2,471.7
XS GIS Cut Line= 3
     1903576.588      436377.177     1903100.025      436556.864
     1902748.463       436804.26
#Sta/Elev= 30
       0 1946.04    29.4 1936.78      49 1931.38    58.8 1929.01    78.4 1924.68
   137.1 1912.82   166.5 1906.41   186.1 1902.85   254.7 1892.74   313.4 1884.72
   362.4 1880.23   401.6 1874.62   411.4 1873.52   519.1 1863.41   538.6 1860.62
  562.21 1854.88   567.9 1853.78   577.7  1853.7  583.321854.775   587.5 1855.57
   597.2 1858.43     607 1860.34   636.3 1863.32   665.6 1865.58   675.4 1866.98
   704.7  1872.6   714.5 1874.77   792.6 1894.28     822 1900.97   939.2 1921.86
#Mann= 3 , 0 , 0
       0      .1       0  562.21    .045       0  583.32      .1       0
Bank Sta=562.21,583.32
XS Rating Curve= 0 ,0
Exp/Cntr=0.3,0.1

Type RM Length L Ch R = 1 ,8476.3  ,518.2,523.3,527.5
XS GIS Cut Line= 3
     1903360.442      436166.239      1903053.15      436145.406
     1902839.608      436127.177
#Sta/Elev= 30
       0 1889.56     9.6 1887.24    19.2 1885.24    28.9 1883.56   125.1 1868.25
   144.4 1865.34     154 1864.03   163.6  1862.9   173.2 1862.02   182.9 1861.38
   202.1 1860.42   211.8 1859.75   221.4 1858.68     231 1856.96   240.6 1854.16
   250.2 1850.91   259.9 1849.57   269.5 1851.62   279.1 1856.43   288.8 1860.95
   298.4 1863.99     308 1866.21   317.7 1867.58   327.5 1868.68   424.9 1878.93
   434.6 1880.09   444.4 1881.94   454.1 1884.93   493.1 1899.05   522.3 1909.17
#Mann= 3 , 0 , 0
       0      .1       0   250.2    .045       0   269.5      .1       0
Bank Sta=250.2,269.5
XS Rating Curve= 0 ,0
Exp/Cntr=0.3,0.1

Type RM Length L Ch R = 1 ,7953    ,590.2,589,587.2
XS GIS Cut Line= 3
     1903495.858      435720.927     1903172.942      435632.385
     1903032.317      435601.135
#Sta/Elev= 30
       0 1889.92    47.8  1879.7    57.4 1877.88      67 1876.53    76.5 1875.51
   114.8 1871.84   153.1 1868.24   200.9  1863.9   210.5 1862.62     220  1860.5
   229.6 1857.75   239.2  1854.6   248.7 1850.96   258.3 1847.57   267.9 1845.95
   277.4 1846.82     287 1849.43   296.6 1852.45   315.7 1857.81   325.3 1861.15
   334.8 1865.02   344.4  1869.2     354 1873.54   363.6 1877.76   373.2 1881.71
   382.8 1885.33   392.5 1888.62   402.1  1891.5   411.7 1893.89   478.9 1908.77
#Mann= 3 , 0 , 0
       0      .1       0   258.3    .045       0   277.4      .1       0
Bank Sta=258.3,277.4
XS Rating Curve= 0 ,0
Exp/Cntr=0.3,0.1

Type RM Length L Ch R = 1 ,7364    ,491.3,494.6,497
XS GIS Cut Line= 3
     1903696.379      435184.468     1903399.504      435124.572
     1903264.088      435093.322
#Sta/Elev= 29
       0 1900.64     9.8 1899.07    19.5 1897.26    39.1 1893.11    58.6 1888.76
    78.2 1884.28   107.5 1877.36   136.8 1870.34   166.1 1863.04   175.8 1860.74
   185.6 1858.59   195.4 1856.79   214.9 1854.04   224.7 1852.36   234.5 1849.52
   244.2 1845.57  250.591843.915     254 1843.03   263.8 1843.55   268.7 1845.02
   273.6 1846.48   283.3 1849.61   293.1 1851.99   312.1 1856.01   321.4 1857.85
   330.6 1859.55   358.4 1864.24   404.8 1871.83   441.8 1877.77
#Mann= 3 , 0 , 0
       0      .1       0  250.59    .045       0   268.7      .1       0
Bank Sta=250.59,268.7
XS Rating Curve= 0 ,0
Exp/Cntr=0.3,0.1

Type RM Length L Ch R = 1 ,6869.4  ,430.2,436.4,442.5
XS GIS Cut Line= 3
     1903712.004      434726.135     1903462.004      434642.802
     1903287.525      434611.552
#Sta/Elev= 25
       0 1871.55    19.5 1867.73    29.3 1866.09      39 1864.72    48.8 1863.48
   107.4 1856.51   126.9 1854.11   156.2 1850.19   175.7 1847.41   195.2 1842.76
     205 1842.14   215.1 1843.73   224.5 1846.18   234.2 1848.26     244 1849.58
   310.2 1856.81   319.5  1857.5   328.8 1857.78   338.2 1858.24   356.8  1860.3
   366.1 1861.25   375.5 1862.42   384.8 1863.84   431.4 1871.54   440.8 1872.88
#Mann= 3 , 0 , 0
       0      .1       0   195.2    .045       0   215.1      .1       0
Bank Sta=195.2,215.1
XS Rating Curve= 0 ,0
Exp/Cntr=0.3,0.1

Type RM Length L Ch R = 1 ,6433    ,376.6,381.4,385.6
XS GIS Cut Line= 3
     1903847.421      434489.156     1903675.546      434369.364
     1903376.067      434168.843
#Sta/Elev= 30
       0 1878.51      19 1873.95    38.1 1869.76    47.6 1867.84    57.1 1865.53
    76.2 1860.03    85.7 1857.51    95.2 1855.33   104.8 1853.59   114.3 1852.18
   133.3 1849.94   152.4 1848.38   161.9 1847.88   209.5 1845.99   238.7  1844.5
   258.2  1843.9   345.9  1842.2   355.6 1841.81  371.821840.752   375.1 1840.58
   384.8 1840.68     393 1841.68   394.6 1841.88   414.1 1846.61   423.8 1848.64
     453 1853.99   472.5 1857.78   482.2 1859.89   511.5 1866.75   569.9 1881.04
#Mann= 3 , 0 , 0
       0      .1       0  371.82    .045       0     393      .1       0
Bank Sta=371.82,393
XS Rating Curve= 0 ,0
Exp/Cntr=0.3,0.1

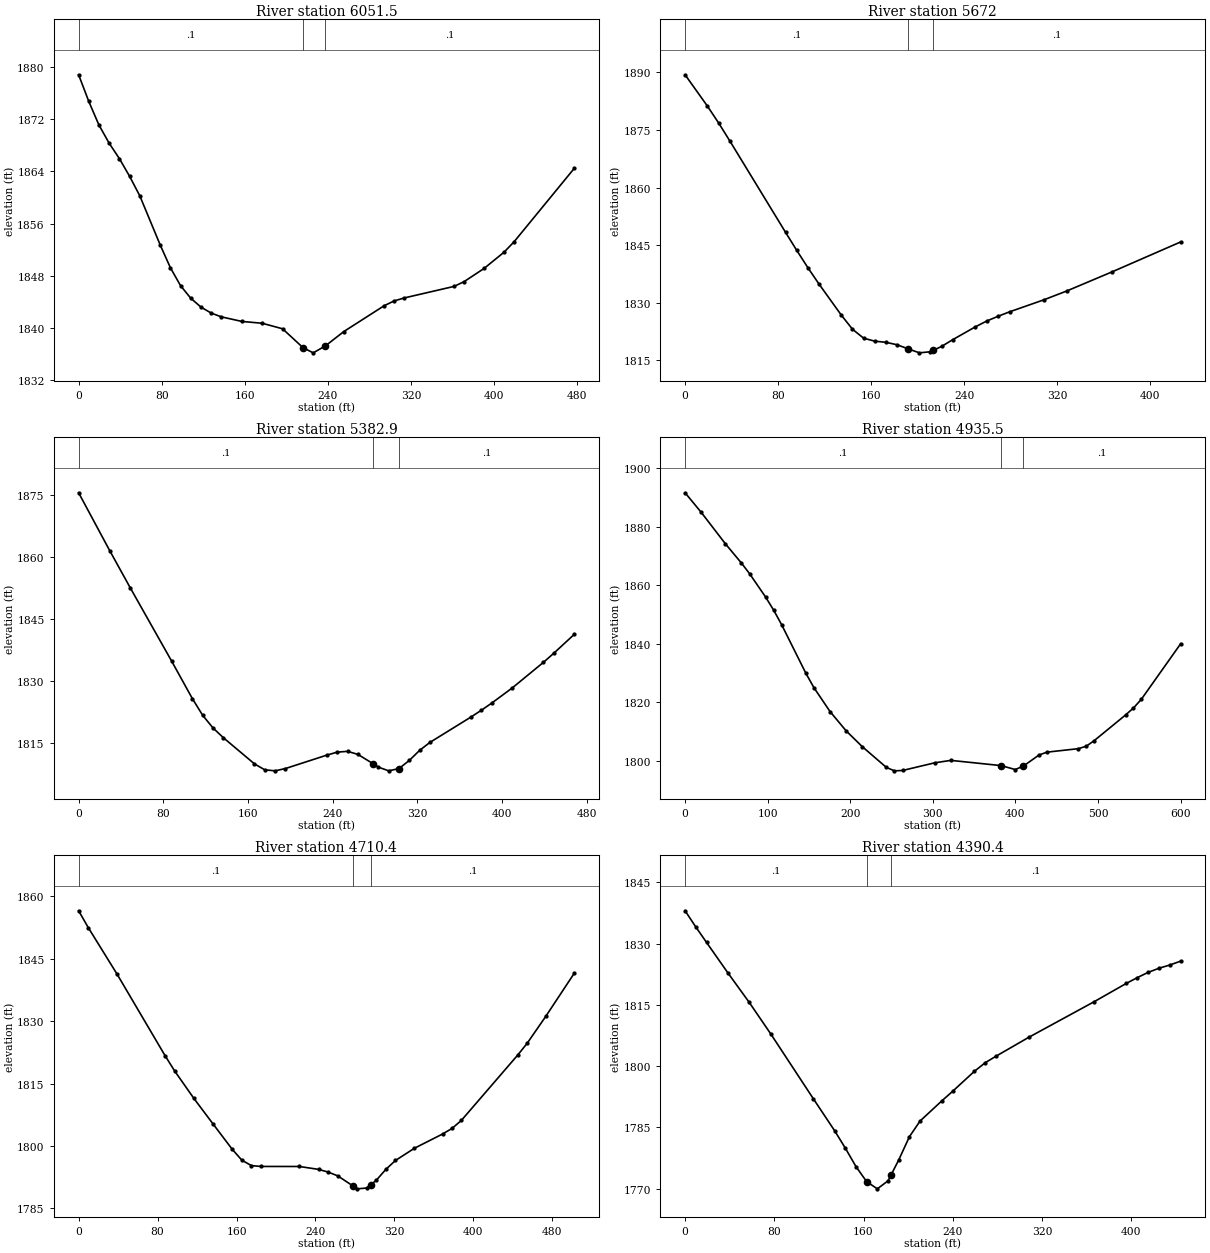
Type RM Length L Ch R = 1 ,6051.5  ,387.3,379.6,372.1
XS GIS Cut Line= 3
     1904006.275      434233.947     1903821.379      434043.843
     1903652.108      433916.239
#Sta/Elev= 30
       0 1878.84     9.8 1874.74    19.6 1871.11    29.5 1868.31    39.3 1865.96
    49.1 1863.25    58.9 1860.26    78.6  1852.7    88.4 1849.21    98.2 1846.46
     108 1844.54   117.9 1843.17   127.7 1842.26   137.5 1841.68   157.2 1840.98
   176.8  1840.7   196.4 1839.85   216.1 1836.95   225.9 1836.16   237.7 1837.23
   255.4 1839.43   294.1 1843.38   303.7 1844.12   313.4 1844.58   361.6 1846.36
   371.2 1847.09   390.4 1849.11   409.7 1851.61   419.4 1853.22   477.2 1864.46
#Mann= 3 , 0 , 0
       0      .1       0   216.1    .045       0   237.7      .1       0
Bank Sta=216.1,237.7
XS Rating Curve= 0 ,0
Exp/Cntr=0.3,0.1

Type RM Length L Ch R = 1 ,5672    ,294,289.1,284.2
XS GIS Cut Line= 3
     1904251.067      433858.947     1904034.921      433754.781
     1903850.025      433731.343
#Sta/Elev= 28
       0  1889.4    19.2 1881.24    28.8 1876.87    38.4  1872.2    86.4 1848.36
      96 1843.68   105.6 1839.15   115.2 1834.88   134.4 1826.78     144 1823.11
   153.6 1820.77   163.2    1820   172.8  1819.7   182.4 1819.06     192 1817.98
   201.6 1816.96   210.9 1817.24  213.271817.578   220.7 1818.64   230.3  1820.4
   249.8 1823.75   259.6 1825.26   269.4 1826.51   279.2 1827.65   308.6 1830.77
   328.2 1833.06   367.5 1838.08   426.3 1845.85
#Mann= 3 , 0 , 0
       0      .1       0     192    .045       0  213.27      .1       0
Bank Sta=192,213.27
XS Rating Curve= 0 ,0
Exp/Cntr=0.3,0.1

Type RM Length L Ch R = 1 ,5382.9  ,434.9,447.4,459.2
XS GIS Cut Line= 3
     1904378.671      433564.677     1904133.879      433496.968
     1903925.546      433447.489
#Sta/Elev= 30
       0 1875.52    29.3 1861.58    48.8 1852.56    87.9 1834.86   107.4 1825.84
   117.2 1821.79     127 1818.72   136.8 1816.37   166.1 1810.07   175.8 1808.64
   185.6 1808.39   195.4 1808.95   234.4 1812.18   244.2  1812.9     254  1813.1
   263.7 1812.37     278 1810.14   283.2 1809.28   292.9 1808.39   302.6 1808.94
   312.4 1810.91   322.1 1813.33   331.8 1815.25   370.8 1821.41   380.5 1823.03
   390.2 1824.74   409.7 1828.42   438.9 1834.55   448.6 1836.72   468.1 1841.32
#Mann= 3 , 0 , 0
       0      .1       0     278    .045       0   302.6      .1       0
Bank Sta=278,302.6
XS Rating Curve= 0 ,0
Exp/Cntr=0.3,0.1

Type RM Length L Ch R = 1 ,4935.5  ,221.7,225.1,228.4
XS GIS Cut Line= 3
     1904591.451      433377.564     1904297.245      433092.634
     1904159.921       432960.51
#Sta/Elev= 30
       0 1891.55    19.5 1884.88    48.8 1874.14    68.3 1867.53      78 1863.96
    97.5 1855.95   107.3 1851.46     117 1846.46   146.3 1829.91     156 1825.03
   175.5 1816.88     195 1810.29   214.5  1804.9   243.8 1797.79   253.5 1796.63
   263.3 1796.75   302.3 1799.37   321.8  1800.2   382.9 1798.41   399.8 1797.07
   409.6 1798.25   428.6 1802.03   438.2 1803.01   476.3  1804.2   485.8 1805.04
   495.3 1806.91   533.4  1815.7     543 1818.09   552.5 1821.05   600.1    1840
#Mann= 3 , 0 , 0
       0      .1       0   382.9    .045       0   409.6      .1       0
#XS Ineff= 2 , 0
          322.52 1800.14
Permanent Ineff=
       F       F
Bank Sta=382.9,409.6
XS Rating Curve= 0 ,0
Exp/Cntr=0.3,0.1

Type RM Length L Ch R = 1 ,4710.4  ,325,320.1,315
XS GIS Cut Line= 3
     1904649.504      433187.072     1904448.983      432924.052
     1904331.796      432799.052
#Sta/Elev= 30
       0 1856.51     9.7 1852.49    38.9  1841.3    87.6 1821.69    97.3 1818.02
   116.7 1811.45   136.2 1805.29   155.6 1799.21   165.4 1796.58   175.1 1795.28
   184.8 1795.08   223.7 1795.07   243.2 1794.37   252.9 1793.72   262.6 1792.81
   277.6 1790.45   282.1  1789.7   291.8 1789.89  295.79 1790.65   301.6 1791.76
   311.3 1794.38     321 1796.51   340.3 1799.46   368.8 1802.88   378.3 1804.21
   387.8 1806.14     445 1821.87   454.5 1824.68   473.5  1831.2   502.1 1841.47
#Mann= 3 , 0 , 0
       0      .1       0   277.6    .045       0  295.79      .1       0
Bank Sta=277.6,295.79
XS Rating Curve= 0 ,0
Exp/Cntr=0.3,0.1

Type RM Length L Ch R = 1 ,4390.4  ,261.4,254.6,247.9
XS GIS Cut Line= 3
     1904886.483      432913.635     1904725.025      432778.218
     1904498.463      432720.927
#Sta/Elev= 30
       0 1838.02     9.6 1834.06    19.2 1830.29    38.3 1822.85    57.5 1815.61
    76.6 1807.98   114.9 1792.07   134.1  1784.2   143.7 1779.94   153.3  1775.4
   162.8 1771.75   172.4 1769.98     182 1771.94   184.5 1773.27   191.6 1777.06
   201.2 1782.75   210.7 1786.57   230.2  1791.5   239.9 1793.84   259.4 1798.73
   269.2 1800.85   278.9 1802.45   308.1 1807.04   366.5 1815.72   395.7 1820.25
   405.5 1821.66   415.2 1822.94     425 1823.96   434.7 1824.75   444.4  1825.7
#Mann= 3 , 0 , 0
       0      .1       0   162.8    .045       0   184.5      .1       0
Bank Sta=162.8,184.5
XS Rating Curve= 0 ,0
Exp/Cntr=0.3,0.1

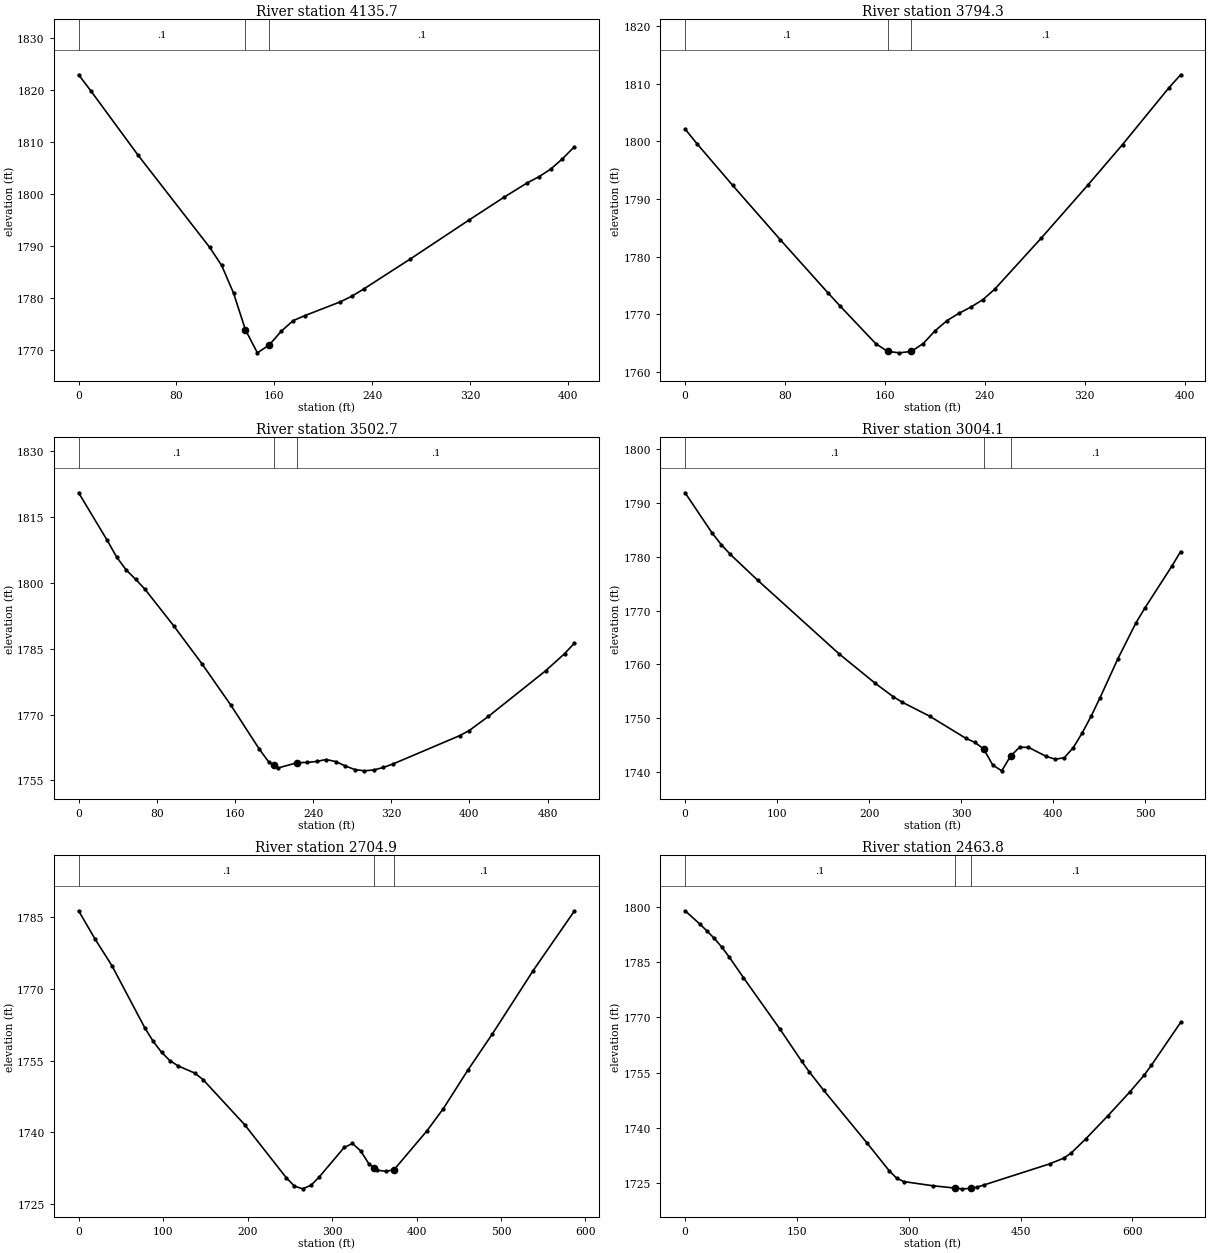
Type RM Length L Ch R = 1 ,4135.7  ,327.2,341.4,355.3
XS GIS Cut Line= 3
     1905055.754      432674.052     1904876.067      432598.531
     1904696.379      432489.156
#Sta/Elev= 23
       0 1822.97     9.8 1819.94    48.7 1807.49   107.2 1789.79     117 1786.32
   126.7 1781.01   136.4 1773.97   146.2 1769.53   155.9 1771.04   165.7 1773.68
   175.4 1775.71   185.2  1776.7     214 1779.33   223.6 1780.44   233.2  1781.8
   271.4 1787.59   319.2 1795.04   347.9 1799.43     367 1802.21   376.6 1803.39
   386.2 1804.86   395.7 1806.82   405.3  1809.1
#Mann= 3 , 0 , 0
       0      .1       0   136.4    .045       0   155.9      .1       0
Bank Sta=136.4,155.9
XS Rating Curve= 0 ,0
Exp/Cntr=0.3,0.1

Type RM Length L Ch R = 1 ,3794.3  ,290.6,291.7,292.6
XS GIS Cut Line= 3
     1905196.379      432502.177     1905066.171      432291.239
     1904977.629      432171.447
#Sta/Elev= 22
       0 1802.15     9.5  1799.6    38.1 1792.37    76.3 1782.92   114.4 1773.72
   123.9 1771.48   152.6 1764.92   162.1 1763.56   171.6 1763.31   181.2 1763.56
   190.7 1764.93   200.2 1767.14   209.8 1768.92   219.3 1770.17   228.8 1771.25
   238.4 1772.53   247.9 1774.35   285.1  1783.2   322.4  1792.4   350.3 1799.46
   387.5 1809.33   396.8 1811.56
#Mann= 3 , 0 , 0
       0      .1       0   162.1    .045       0   181.2      .1       0
Bank Sta=162.1,181.2
XS Rating Curve= 0 ,0
Exp/Cntr=0.3,0.1

Type RM Length L Ch R = 1 ,3502.7  ,499.5,498.5,496.7
XS GIS Cut Line= 3
     1905472.169      432446.111     1905425.294       432339.34
      1905235.19      431998.194
#Sta/Elev= 30
       0 1820.57    29.2 1809.75    38.9 1805.93    48.6 1802.99    58.3 1800.86
      68 1798.55    97.2 1790.28   126.4 1781.54   155.7 1772.19     185 1762.11
   194.7 1759.17  200.011758.466   204.5 1757.87     224 1759.06   233.8  1759.1
   243.5 1759.33   253.3 1759.77   263.1 1759.31   272.8 1758.32   282.6 1757.49
   292.4 1757.19   302.1 1757.39   311.9 1757.96   321.6 1758.74     390 1765.21
   399.8 1766.38   419.3 1769.58   477.9 1779.98   497.4  1783.9   507.2 1786.24
#Mann= 3 , 0 , 0
       0      .1       0  200.01    .045       0     224      .1       0
Bank Sta=200.01,224
XS Rating Curve= 0 ,0
Exp/Cntr=0.3,0.1

Type RM Length L Ch R = 1 ,3004.1  ,290.9,299.2,307.3
XS GIS Cut Line= 3
     1905790.129      432239.156     1905719.817      431942.281
     1905592.213      431746.968
#Sta/Elev= 30
       0 1791.92    29.5  1784.4    39.4 1782.25    49.2 1780.45    78.7 1775.68
   167.3 1761.96   206.7 1756.47   226.4 1753.96   236.2 1752.94   265.7 1750.37
   305.1 1746.24   314.8  1745.5   324.5 1744.24   334.2 1741.29     344  1740.2
   353.7 1742.96   363.4 1744.59   373.1 1744.57   392.6 1742.87   402.3 1742.36
     412 1742.64   421.7  1744.5   431.5 1747.26   441.2 1750.38   450.9 1753.83
   470.3 1761.08   489.8 1767.71   499.5 1770.48   528.7 1778.23   538.4 1780.99
#Mann= 3 , 0 , 0
       0      .1       0   324.5    .045       0   353.7      .1       0
Bank Sta=324.5,353.7
XS Rating Curve= 0 ,0
Exp/Cntr=0.3,0.1

Type RM Length L Ch R = 1 ,2704.9  ,248.5,241.1,233.2
XS GIS Cut Line= 3
     1905995.858      432111.552     1905917.733      431736.552
     1905860.442      431541.239
#Sta/Elev= 30
       0 1786.37    19.6  1780.4    39.3 1774.92    78.6 1761.79    88.4 1759.02
    98.2 1756.75     108 1755.02   117.9  1753.9   137.5 1752.41   147.3 1751.04
   196.4 1741.64   245.6 1730.56   255.4 1728.77   265.2 1728.19     275 1728.93
   284.8 1730.67   314.3 1736.84   324.1 1737.68   333.9 1736.13   343.8 1733.36
   350.21732.537   353.6  1732.1   363.4 1731.86   373.2 1732.16   412.1 1740.28
   431.5 1744.92   460.6 1752.99   489.7 1760.58   538.1 1773.87   586.6 1786.26
#Mann= 3 , 0 , 0
       0      .1       0   350.2    .045       0   373.2      .1       0
#XS Ineff= 2 , 0
          307.79 1735.05
Permanent Ineff=
       F       F
Bank Sta=350.2,373.2
XS Rating Curve= 0 ,0
Exp/Cntr=0.3,0.1

Type RM Length L Ch R = 1 ,2463.8  ,296.3,277.4,259.3
XS GIS Cut Line= 3
     1906350.459      432080.649     1906163.256      431759.675
     1906004.973       431512.94
#Sta/Elev= 30
       0 1798.85    19.6 1795.29    29.3  1793.4    39.1 1791.38    48.9 1789.09
    58.7 1786.46    78.2 1780.76   127.1 1766.84   156.4 1758.08   166.2 1755.31
   185.8 1750.25   244.5 1735.83   273.8 1728.42   283.6 1726.43   293.4 1725.49
   332.5 1724.36   361.8 1723.74   371.6 1723.53  382.981723.636   391.1 1723.97
   400.9 1724.58   488.8 1730.28   508.4 1731.89   518.2 1733.29   537.7 1737.12
     567  1743.3   596.3 1749.73   615.9 1754.34   625.6 1757.04   664.7 1768.61
#Mann= 3 , 0 , 0
       0      .1       0   361.8    .045       0  382.98      .1       0
Bank Sta=361.8,382.98
XS Rating Curve= 0 ,0
Exp/Cntr=0.3,0.1