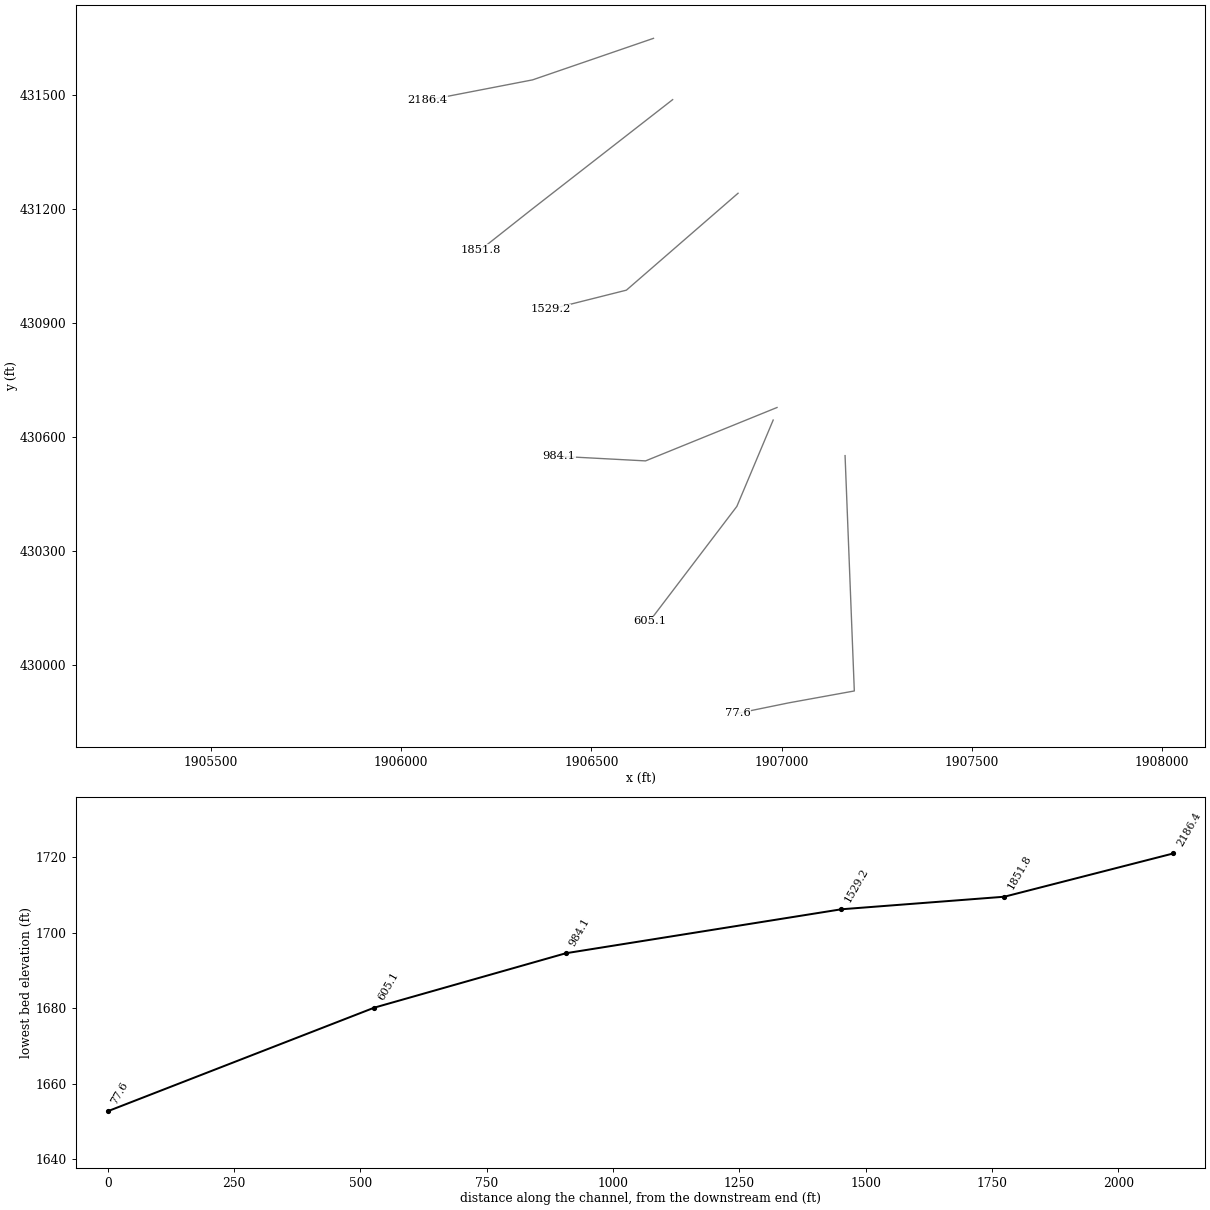
HEC-RAS study PATTERSNRN.prj: PATTERSNRN

--- PATTERSNRN.g01 (geometry) --- (continued)

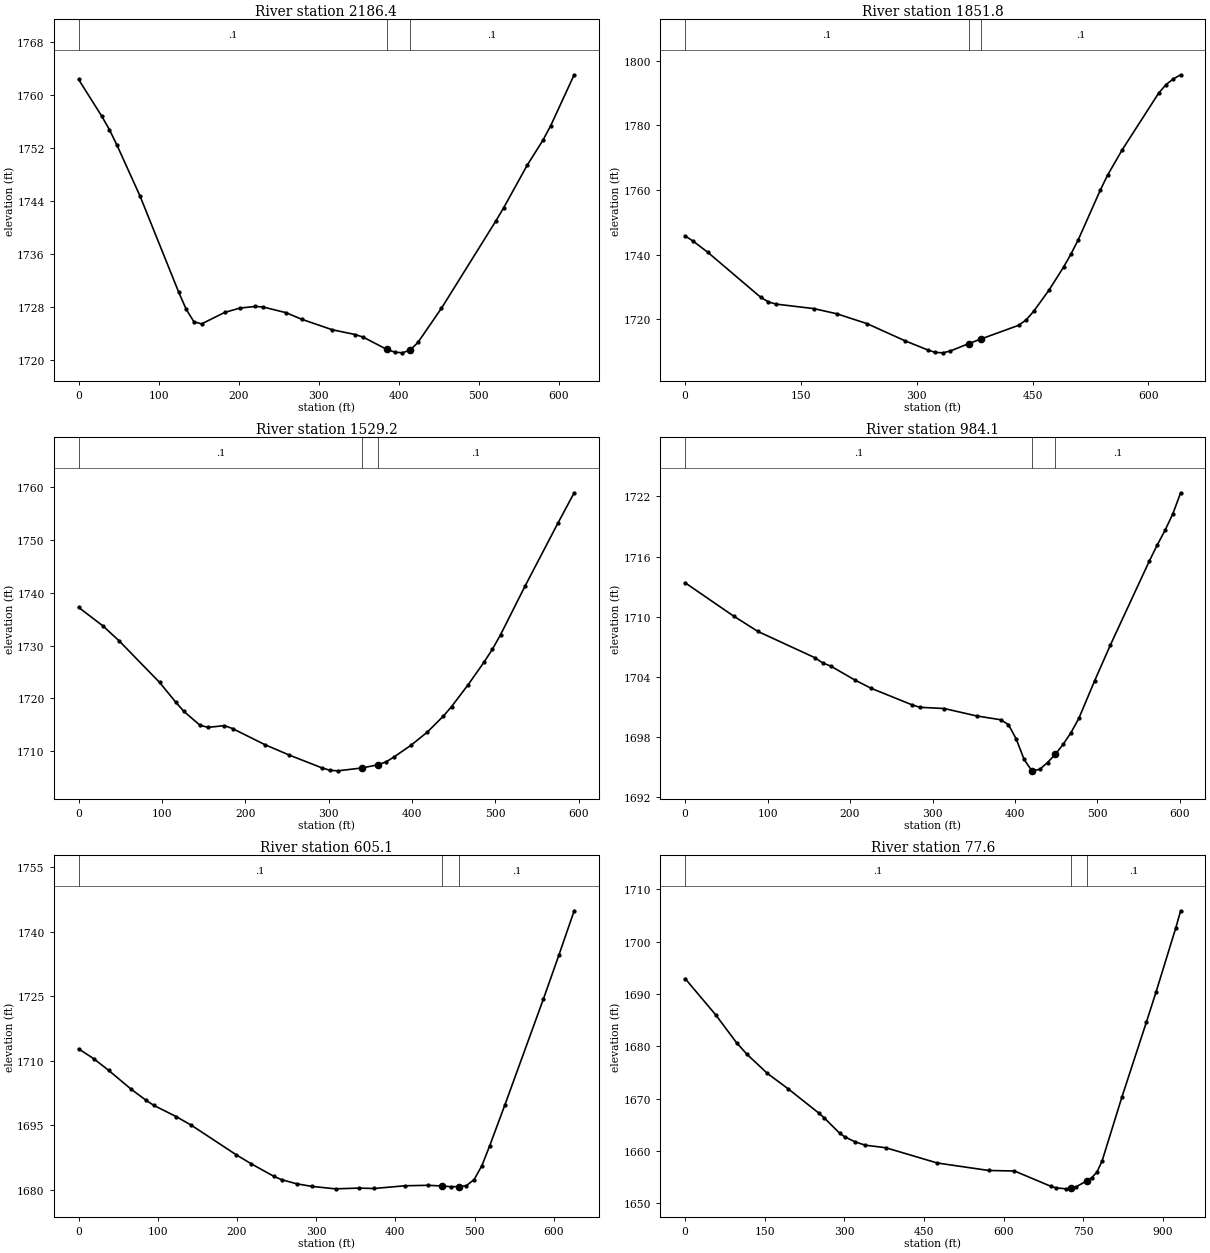
Type RM Length L Ch R = 1 ,2186.4  ,323.9,334.6,344.8
XS GIS Cut Line= 3
     1906662.959      431650.093     1906345.251      431540.718
     1906067.473      431486.899
#Sta/Elev= 30
       0 1762.28    28.8 1756.76    38.4 1754.74      48 1752.35    76.8 1744.68
   124.8 1730.28   134.4 1727.63     144 1725.77   153.6 1725.44   182.4 1727.17
   201.6 1727.83   220.8 1728.07   230.4 1727.99   259.2 1727.13   278.4 1726.15
   316.8 1724.56   345.8 1723.83   355.5 1723.44   384.8 1721.61   394.6  1721.2
   404.3 1721.08   414.1  1721.5   423.8 1722.64   453.1 1727.78   521.4    1741
   531.1 1742.98   560.4 1749.38   579.9 1753.11   589.7 1755.32     619 1762.99
#Mann= 3 , 0 , 0
       0      .1       0   384.8    .045       0   414.1      .1       0
Bank Sta=384.8,414.1
XS Rating Curve= 0 ,0
Exp/Cntr=0.3,0.1

Type RM Length L Ch R = 1 ,1851.8  ,321.2,322.6,324.1
XS GIS Cut Line= 3
     1906713.306      431488.635     1906341.779      431198.704
     1906208.098      431092.802
#Sta/Elev= 30
       0 1745.76     9.8 1744.28    29.4 1740.71    98.2 1726.73     108 1725.35
   117.8 1724.68   166.9 1723.28   196.4 1721.69   235.6 1718.64   284.7 1713.34
   314.2  1710.5     324 1709.74   333.8  1709.6   343.6 1710.18   367.2 1712.44
   382.9 1713.86     432 1718.12   441.8 1719.81   451.6  1722.5   471.3 1729.01
   490.2 1736.15   499.7 1740.14   509.2 1744.59   537.6 1759.87   547.1 1764.54
     566 1772.38   613.4 1789.99   622.9 1792.61   632.3 1794.35   641.8 1795.64
#Mann= 3 , 0 , 0
       0      .1       0   367.2    .045       0   382.9      .1       0
Bank Sta=367.2,382.9
XS Rating Curve= 0 ,0
Exp/Cntr=0.3,0.1

Type RM Length L Ch R = 1 ,1529.2  ,562.5,545.1,527.1
XS GIS Cut Line= 3
     1906885.181      431242.107     1906591.779      430986.899
     1906392.126      430936.552
#Sta/Elev= 30
       0 1737.25    29.2 1733.73    48.6 1730.91    97.2 1723.02   116.7 1719.26
   126.4 1717.53   145.8 1714.89   155.6 1714.51     175 1714.84   184.7 1714.29
   223.6 1711.23   252.8 1709.26   291.6 1706.86   301.4 1706.38   311.1 1706.27
   340.3 1706.82   359.7 1707.43   369.4    1708   379.1 1708.96   398.7 1711.09
   418.3 1713.58   437.9 1716.66   447.7 1718.46   467.3 1722.54   486.9 1726.94
   496.7 1729.33   506.5 1732.09   535.9 1741.31   575.2 1753.19   594.8 1758.97
#Mann= 3 , 0 , 0
       0      .1       0   340.3    .045       0   359.7      .1       0
Bank Sta=340.3,359.7
XS Rating Curve= 0 ,0
Exp/Cntr=0.3,0.1

Type RM Length L Ch R = 1 ,984.1   ,357,379,401.1
XS GIS Cut Line= 3
     1906987.612      430677.871     1906642.126      430537.246
     1906414.695      430549.399
#Sta/Elev= 30
       0 1713.39    58.9 1710.06    88.3 1708.53   157.1 1705.92   166.9 1705.39
   176.7 1705.07   206.1 1703.67   225.8 1702.85   274.8 1701.22   284.7 1700.96
   314.1 1700.84   353.4  1700.1   382.5 1699.72     392 1699.24   401.5 1697.79
     411 1695.76   420.5 1694.62     430 1694.77   439.4 1695.45   448.9 1696.27
   458.4 1697.27   467.9 1698.44   477.4 1699.86   496.4 1703.58   515.4 1707.14
   562.8 1715.55   572.3 1717.14   581.8 1718.61   591.3 1720.26   600.8 1722.37
#Mann= 3 , 0 , 0
       0      .1       0   420.5    .045       0   448.9      .1       0
Bank Sta=420.5,448.9
XS Rating Curve= 0 ,0
Exp/Cntr=0.3,0.1

Type RM Length L Ch R = 1 ,605.1   ,544.2,527.5,509.9
XS GIS Cut Line= 3
     1906977.542      430644.841     1906882.056      430417.411
      1906652.89      430115.328
#Sta/Elev= 30
       0 1712.75      19 1710.48      38 1707.74    66.4 1703.36    85.4 1700.76
    94.9 1699.62   123.3 1696.99   142.3    1695   199.2  1688.1   218.2    1686
   246.7 1683.09   256.4 1682.33   275.8 1681.35   295.3 1680.75   324.4  1680.2
   353.6 1680.37     373 1680.28   411.9 1680.91   441.1 1681.02   458.5 1680.87
   470.3  1680.7     480 1680.72   489.7 1680.95   499.4 1682.35   509.2 1685.56
   518.9 1690.11   538.3 1699.72     587 1724.38   606.4 1734.51   625.8 1744.87
#Mann= 3 , 0 , 0
       0      .1       0   458.5    .045       0     480      .1       0
Bank Sta=458.5,480
XS Rating Curve= 0 ,0
Exp/Cntr=0.3,0.1

Type RM Length L Ch R = 1 ,77.6    ,88.5,77.6,66.2
XS GIS Cut Line= 4
     1907166.431      430551.135     1907190.737      429931.343
     1907018.862      429900.093     1906883.445      429872.315
#Sta/Elev= 30
       0 1692.95    58.2 1685.94    96.9 1680.68   116.3 1678.49   155.1  1674.8
   193.8 1671.89     252 1667.21   261.7 1666.34   290.8  1663.4   300.4  1662.7
   319.8 1661.74   339.2 1661.09     378  1660.6   474.9 1657.68   571.8 1656.25
   620.3 1656.15   688.2 1653.25   697.9 1652.94   717.3 1652.74     727 1652.84
   736.7 1653.15   756.1 1654.24   765.8 1654.88   775.6 1655.94   785.3 1658.08
   822.6 1670.29   868.7 1684.61   887.1 1690.45     924 1702.61   933.2 1705.91
#Mann= 3 , 0 , 0
       0      .1       0     727    .045       0   756.1      .1       0
Bank Sta=727,756.1
XS Rating Curve= 0 ,0
Exp/Cntr=0.3,0.1

Chan Stop Cuts=-1
Use User Specified Reach Order=0
Composite Channel Slope=5